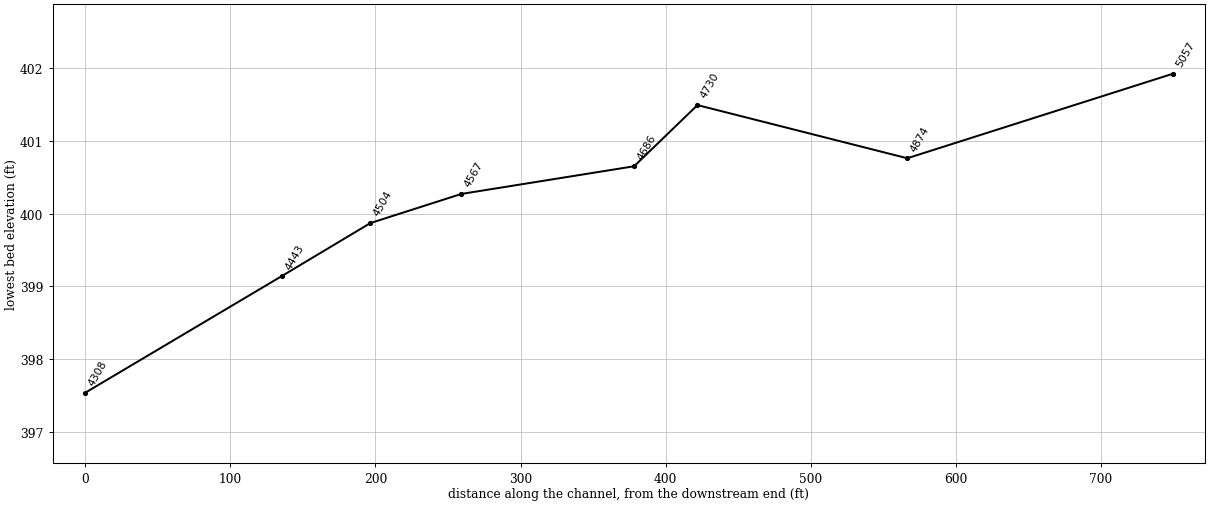
--- FayetteCo.prj (project) ---

Proj Title=Fayette Co
Current Plan=p07
Default Exp/Contr=0.3,0.1
English Units
Geom File=g01
Geom File=g02
Geom File=g05
Geom File=g07
Geom File=g08
Flow File=f01
Flow File=f02
Flow File=f03
Plan File=p01
Plan File=p02
Plan File=p06
Plan File=p07
Plan File=p08
Y Axis Title=Elevation
X Axis Title(PF)=Main Channel Distance
X Axis Title(XS)=Station
BEGIN DESCRIPTION:
END DESCRIPTION:
DSS File=dss
DSS Export Rating Curves= 0
DSS Export Rating Curve Sorted= 0
DSS Export Volume Flow Curves= 0
DXF Filename=..\..\..\TDOT - Bridges - HEC-RAS\HEC-RAS\Fayette Co\Fayette Co HEC-RAS\FayetteCo.
DXF OffsetX= 0
DXF OffsetY= 0
DXF ScaleX= 1
DXF ScaleY= 10

--- FayetteCo.p07 (plan) ---

Plan Title=EXISTING - mod 1-21-2020
Program Version=5.07
Short Identifier=EX_MOD_1-21-2020
Geom File=g08
Flow File=f01
Subcritical Flow
K Sum by GR= 0
Std Step Tol= 0.01
Critical Tol= 0.01
Num of Std Step Trials= 20
Max Error Tol= 0.3
Flow Tol Ratio= 0.001
Split Flow NTrial= 30
Split Flow Tol= 0.02
Split Flow Ratio= 0.02
Log Output Level= 0
Friction Slope Method= 1
Unsteady Friction Slope Method= 2
Unsteady Bridges Friction Slope Method= 1
Parabolic Critical Depth
Global Vel Dist= 0 , 0 , 0
Global Log Level= 0
CheckData=True
Encroach Param=-1 ,0,0, 0
Computation Interval=1MIN
Output Interval=1HOUR
Instantaneous Interval=1HOUR
Mapping Interval=1HOUR
Computation Time Step Use Courant=        0
Computation Time Step Use Time Series=    0
Computation Time Step Count To Double=0
Computation Time Step Max Doubling=0
Computation Time Step Max Halving=0
Computation Time Step Residence Courant=0
Run HTab= 0
Run UNet= 0
Run Sediment= 0
Run PostProcess= 0
Run WQNet= 0
Run RASMapper= 0
UNET Theta= 1
UNET Theta Warmup= 1
UNET ZTol= 0.02
UNET ZSATol= 0.02
UNET MxIter= 20
UNET Max Iter WO Improvement= 0
UNET MaxInSteps= 0
UNET DtIC= 0
UNET DtMin= 0
UNET MaxCRTS= 20
UNET WFStab= 2
UNET SFStab= 1
UNET WFX= 1
UNET SFX= 1
UNET 1D Methodology=Finite Difference
UNET DSS MLevel= 4
UNET Pardiso=0
UNET DZMax Abort= 100
UNET Use Existing IB Tables=-1
UNET Froude Reduction=False
UNET Froude Limit= 0.8
UNET Froude Power= 4
UNET D1 Cores= 0
UNET D2 Coriolis=0
UNET D2 Cores= 0
UNET D2 Theta= 1
UNET D2 Theta Warmup= 1
UNET D2 Z Tol= 0.01
UNET D2 Volume Tol= 0.01
UNET D2 Max Iterations= 20
UNET D2 Equation= 0
UNET D2 RampUpFraction=0.1
UNET D2 TimeSlices= 1
UNET D2 BCVolumeCheck=0
UNET D1D2 MaxIter= 0
UNET D1D2 ZTol=0.01
UNET D1D2 QTol=0.1
UNET D1D2 MinQTol=1
DSS File=dss
Write IC File= 0
Write IC File at Fixed DateTime=0
Write IC File at Sim End=0
Echo Input=False
Echo Parameters=False
Echo Output=False
Write Detailed= 0
HDF Write Warmup=0
HDF Write Time Slices=0
HDF Flush=0
HDF Face Node Velocities=0
HDF Compression= 1
HDF Chunk Size= 1
HDF Spatial Parts= 1
HDF Use Max Rows=0
HDF Fixed Rows= 1
Calibration Method= 0
Calibration Iterations= 20
Calibration Max Change=0.05
Calibration Tolerance=0.2
Calibration Maximum=1.5
Calibration Minimum=0.5
Calibration Optimization Method= 1
WQ AD Non Conservative
WQ ULTIMATE=-1
WQ Max Comp Step=1HOUR
WQ Output Interval=15MIN
WQ Output Selected Increments= 0
WQ Output face flow=0
WQ Output face velocity=0
WQ Output face area=0
WQ Output face dispersion=0
WQ Output cell volume=0
WQ Output cell surface area=0
WQ Output cell continuity=0
WQ Output cumulative cell continuity=0
WQ Output face conc=0
WQ Output face dconc_dx=0
WQ Output face courant=0
WQ Output face peclet=0
WQ Output face adv mass=0
WQ Output face disp mass=0
WQ Output cell mass=0
WQ Output cell source sink temp=0
WQ Output nsm pathways=0
WQ Output nsm derived pathways=0
WQ Output MaxMinRange=-1
WQ Daily Max Min Mean=-1
WQ Daily Range=0
WQ Daily Time=0
WQ Create Restart=0
WQ Fixed Restart=0
WQ System Summary=0
WQ Write To DSS=0
WQ Use Fixed Temperature=0
Sorting and Armoring Iterations= 10
XS Update Threshold= 0.02
Bed Roughness Predictor= 0
Hydraulics Update Threshold= 0.02
Energy Slope Method= 1
Volume Change Method= 1
Sediment Retention Method= 0
XS Weighting Method= 0
Number of US Weighted Cross Sections= 1
Number of DS Weighted Cross Sections= 1
Upstream XS Weight=0
Main XS Weight=1
Downstream XS Weight=0
Number of DS XS's Weighted with US Boundary= 1
Upstream Boundary Weight= 1
Weight of XSs Associated with US Boundary= 0
Number of US XS's Weighted with DS Boundary= 1
Downstream Boundary Weight= 0.5
Weight of XSs Associated with DS Boundary= 0.5
Percentile Method= 0
Sediment Output Level= 3
Mass or Volume Output= 0
Output Increment Type= 1
Profile and TS Output Increment= 1
XS Output Flag= 0
XS Output Increment= 10
Write Gradation File= 0
Read Gradation Hotstart= 0
Write HDF5 File= 1
Write Binary Output= 1
Write DSS Sediment File= 0
SV Curve= 0
Specific Gage Flag= 0

--- FayetteCo.p01 (plan) ---

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Plan Title=NATURAL
Program Version=5.06
Short Identifier=NATURAL
Geom File=g02
Flow File=f01

--- FayetteCo.p02 (plan) ---

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Plan Title=EXISTING
Program Version=5.06
Short Identifier=EXISTING
Geom File=g01
Flow File=f01

--- FayetteCo.p06 (plan) ---

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Plan Title=PROPOSED
Program Version=5.06
Short Identifier=PROPOSED
Geom File=g05
Flow File=f01

--- FayetteCo.p08 (plan) ---

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Plan Title=PROPOSED - mod 1-21-2020
Short Identifier=PR_MOD_1-21-2020
Geom File=g07
Flow File=f01

--- FayetteCo.f01 (steady flow) ---

Flow Title=FayetteCoFlowData
Program Version=5.06
BEGIN FILE DESCRIPTION:
Unnamed Branch of Shaws Creek
END FILE DESCRIPTION:
Number of Profiles= 7
Profile Names=Q2,Q5,Q10,Q25,Q50,Q100,Q500
River Rch & RM=Branch of Shaws,Branch          ,5057
     469     667     794     950    1060    1170    1420
Boundary for River Rch & Prof#=Branch of Shaws,Branch          , 1
Up Type= 0
Dn Type= 3
Dn Slope=0.00585
Boundary for River Rch & Prof#=Branch of Shaws,Branch          , 2
Up Type= 0
Dn Type= 3
Dn Slope=0.00585
Boundary for River Rch & Prof#=Branch of Shaws,Branch          , 3
Up Type= 0
Dn Type= 3
Dn Slope=0.00585
Boundary for River Rch & Prof#=Branch of Shaws,Branch          , 4
Up Type= 0
Dn Type= 3
Dn Slope=0.00585
Boundary for River Rch & Prof#=Branch of Shaws,Branch          , 5
Up Type= 0
Dn Type= 3
Dn Slope=0.00585
Boundary for River Rch & Prof#=Branch of Shaws,Branch          , 6
Up Type= 0
Dn Type= 3
Dn Slope=0.00585
Boundary for River Rch & Prof#=Branch of Shaws,Branch          , 7
Up Type= 0
Dn Type= 3
Dn Slope=0.00585
DSS Import GetInterval= 0
DSS Import GetPeak= 0
DSS Import FillOption= 0

--- FayetteCo.f02 (steady flow) ---

Flow Title=Flow 02
Program Version=5.06
Number of Profiles= 1
Profile Names=PF 1
DSS Import GetInterval= 0
DSS Import GetPeak= 0
DSS Import FillOption= 0

--- FayetteCo.f03 (steady flow) ---

Flow Title=Flow 03
Program Version=5.06
Number of Profiles= 1
Profile Names=PF 1
DSS Import GetInterval= 0
DSS Import GetPeak= 0
DSS Import FillOption= 0

--- FayetteCo.g08 (geometry) ---

Geom Title=EXISTING - mod 1-21-2020
Program Version=5.07

River Reach=Branch of Shaws ,Branch
Reach XY= 2
0.714730290456430.641078838174270.287344398340250.31742738589212

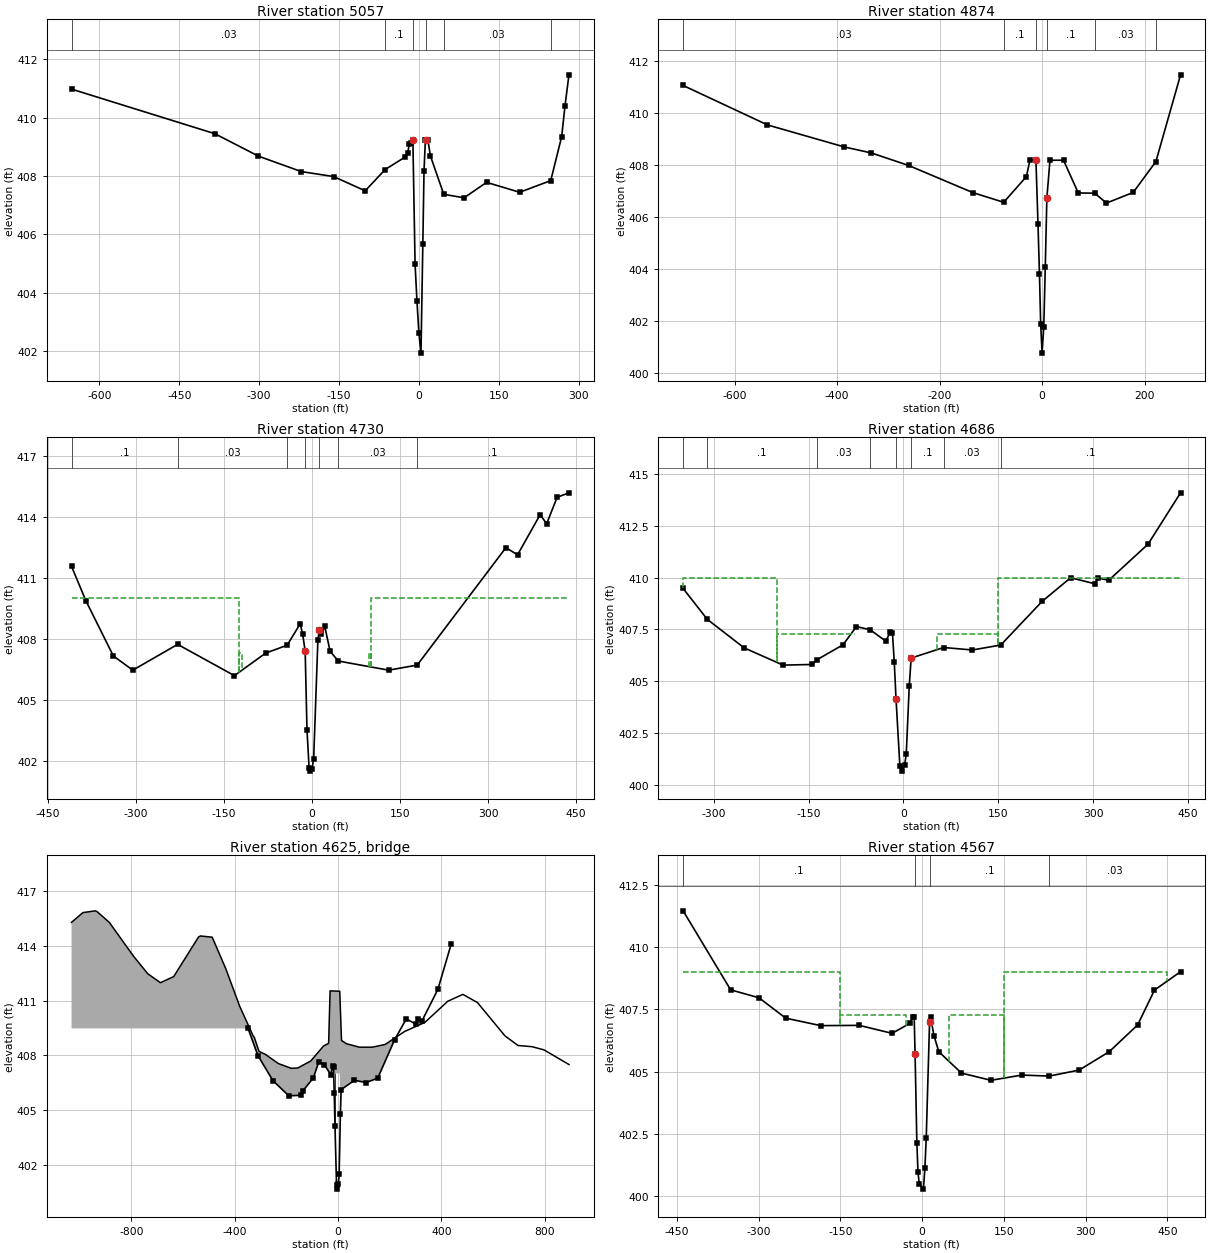
Type RM Length L Ch R = 1 ,5057    ,190.75,182.96,174.42
BEGIN DESCRIPTION:
5057
END DESCRIPTION:
#Sta/Elev= 30
 -652.41  410.98 -383.33  409.45 -301.37  408.68 -220.99  408.15 -160.36  407.98
 -100.86  407.49  -63.38  408.22  -25.79  408.65  -21.04   408.8  -17.95  409.08
  -13.94  409.12  -11.29  409.23   -7.18  404.98   -3.66  403.72       0  402.61
    3.93  401.92    7.41  405.68    9.63  408.18    12.2  409.23   14.26  409.23
   16.97  409.23   21.59  408.69   46.72  407.37   84.82  407.25  127.13  407.78
  189.23  407.44  247.63  407.84  268.17  409.35  274.45  410.41  281.85  411.47
#Mann= 6 ,-1 , 0
 -652.41     .03       0  -63.38      .1       0  -11.29    .035       0
   14.26      .1       0   46.72     .03       0  247.63      .1       0
Bank Sta=-11.29,14.26
XS Rating Curve= 0 ,0
Exp/Cntr=0.3,0.1

Type RM Length L Ch R = 1 ,4874    ,141.25,144.57,149.21
BEGIN DESCRIPTION:
4874
END DESCRIPTION:
#Sta/Elev= 25
 -700.58  411.07 -535.93  409.55 -385.67   408.7 -333.05  408.47 -260.66  407.99
  -134.7  406.94  -74.86  406.57  -30.62  407.56   -23.7  408.19  -11.99  408.19
   -7.96  405.74   -5.07  403.79   -2.76   401.9       0  400.76    3.34  401.77
    6.24  404.06    9.34  406.73   15.42  408.19   41.91  408.19   70.61  406.93
  102.84  406.92   125.6  406.54  177.91  406.95  222.18  408.14  270.27  411.48
#Mann= 6 ,-1 , 0
 -700.58     .03       0  -74.86      .1       0  -11.99    .035       0
    9.34      .1       0  102.84     .03       0  222.18      .1       0
Bank Sta=-11.99,9.34
XS Rating Curve= 0 ,0
Exp/Cntr=0.3,0.1

Type RM Length L Ch R = 1 ,4730    ,38.58,43.64,47.98
BEGIN DESCRIPTION:
4730 - BR CS #4
END DESCRIPTION:
#Sta/Elev= 30
 -409.98  411.57 -385.41  409.87 -338.72  407.16 -305.56  406.46 -229.16  407.73
 -132.38  406.19   -79.1   407.3  -42.39  407.69  -20.42  408.74   -16.1  408.25
  -11.78  407.38    -8.7  403.53   -5.09  401.64   -3.15  401.49       0   401.6
    2.71  402.11    9.91  407.96    12.3  408.42   15.84  408.22   21.67  408.61
   30.67  407.39   44.71  406.91  130.41  406.46  179.15  406.71   330.3  412.49
   350.2  412.14  388.59  414.11  399.86  413.67  417.57  414.97  437.78  415.19
#Mann= 7 ,-1 , 0
 -409.98      .1       0 -229.16     .03       0  -42.39      .1       0
  -11.78    .035       0    12.3      .1       0   44.71     .03       0
  179.15      .1       0
#XS Ineff= 4 ,-1
    -410    -125     410    -125-120.305  407.29   97.23     100  407.29
     100     450     410
Permanent Ineff=
       F       F       F       F
Bank Sta=-11.78,12.3
XS Rating Curve= 0 ,0
Exp/Cntr=0.5,0.3

Type RM Length L Ch R = 1 ,4686    ,120.89,119.06,117.02
BEGIN DESCRIPTION:
4686 - BR CS #3
END DESCRIPTION:
#Sta/Elev= 30
 -348.15  409.47 -309.97  407.98 -251.64   406.6  -190.2  405.77 -143.96   405.8
 -137.18  406.02  -95.52  406.75  -74.35  407.63  -52.75  407.48  -27.64  406.92
  -20.97  407.39  -17.38  407.33  -14.55  405.93  -11.73  404.14   -5.68   400.9
   -2.02  400.65    1.81  400.94    4.42  401.47    9.16  404.76   12.14  406.11
   63.56  406.62  108.87   406.5  153.75  406.74  219.21  408.85  264.19  409.99
   302.2   409.7  307.65  409.97  324.49  409.87  386.49  411.61  437.85  414.09
#Mann= 8 ,-1 , 0
 -348.15     .03       0 -309.97      .1       0 -137.18     .03       0
  -52.75      .1       0  -11.73    .035       0   12.14      .1       0
   63.56     .03       0  153.75      .1       0
#XS Ineff= 4 ,-1
    -400    -200     410    -200 -76.305  407.29   53.23     150  407.29
     150     450     410
Permanent Ineff=
       F       F       F       F
Bank Sta=-11.73,12.14
XS Rating Curve= 0 ,0
Exp/Cntr=0.5,0.3

Type RM Length L Ch R = 3 ,4625    ,,,
Bridge Culvert--1,0,-1,-1, 0
Deck Dist Width WeirC Skew NumUp NumDn MinLoCord MaxHiCord MaxSubmerge Is_Ogee
45.85,30.78,2.6,0, 41, 38, , , 0.98, 0, 3,5,,
-1031.15 -987.16 -939.16 -932.12 -885.08 -790.09 -736.09 -687.05 -635.74 -540.02
 -532.39  -486.8 -434.18 -380.57 -328.17 -324.03 -305.63 -280.63 -230.63 -180.63
 -155.63 -105.63  -55.63  -36.31  -30.63    6.81   13.59   32.55   82.55  132.55
  182.55  257.55  335.88  424.94   483.2  539.68  646.14  696.73   750.8   796.8
  893.74
 415.293 415.826 415.923 415.878  415.29 413.412 412.469 411.978 412.316 414.481
 414.544 414.477 412.745 410.691 409.055 408.985  408.21  408.04  407.54  407.28
   407.3  407.68  408.51  408.65  411.53  411.51  408.81  408.63  408.44  408.44
  408.59   409.3 409.797 410.961 411.337 410.889  409.06 408.532 408.467 408.294
 407.489
     350     350     350     350     350     350     350     350     350     350
     350     350     350     350     350     350     350     350     350     350
     350     350     350     350     407     407     350     350     350     350
     350     350     350     350     350     350     350     350     350     350
     350
-1009.45 -965.46 -917.46 -910.42 -863.38 -768.39 -714.39 -665.35 -614.04 -518.32
 -510.69  -465.1 -412.48 -358.87 -281.96 -256.96 -206.96 -156.96 -131.96  -81.96
  -14.61   -8.76  29.075   35.29   56.22  106.22  156.22  206.22  281.22  357.58
  446.64   504.9  561.38  667.84  718.43   772.5   818.5  915.44
 415.293 415.826 415.923 415.878  415.29 413.412 412.469 411.978 412.316 414.481
 414.544 414.477 412.745 410.691  408.21  408.04  407.54  407.28   407.3  407.68
  408.82  411.53 411.504  408.81  408.63  408.44  408.44  408.59   409.3 409.797
 410.961 411.337 410.889  409.06 408.532 408.467 408.294 407.489
     350     350     350     350     350     350     350     350     350     350
     350     350     350     350     350     350     350     350     350     350
     350     407     407     350     350     350     350     350     350     350
     350     350     350     350     350     350     350     350
Pier Skew, UpSta & Num, DnSta & Num=  ,-10.85, 2 ,10.85, 2 , 0 , 0 , 0 ,,
       1       1
     350     407
       1       1
     350     407
BR Coef=-1 , 0 , 0 ,, 0 ,,,0.8,-1,,0,
WSPro=,,,, 1 ,,,, 0 ,,,, 0 ,,,,-1 ,-1 ,-1 , 0 , 0 , 0 , 0 , 0
BC Design=,, 0 ,, 0 ,,,,,,
BC Use User HTab Curves=0
BC User HTab FreeFlow(D)= 0

Type RM Length L Ch R = 1 ,4567    ,62.66,62.69,63.44
BEGIN DESCRIPTION:
4567 - BR CS #2
END DESCRIPTION:
#Sta/Elev= 30
 -438.38  411.47 -351.23  408.29 -299.17  407.97 -250.17  407.15 -185.97  406.85
 -115.25  406.86  -54.99  406.54  -21.79  406.95   -17.4   407.2  -14.48   407.2
  -12.83  405.69   -9.58  402.14   -7.56  400.96   -5.23  400.49    2.42  400.27
     5.2  401.12    7.65  402.34   13.75     407   15.57   407.2   21.87  406.44
   30.73   405.8   72.16  404.94  126.33  404.65  182.98  404.86   233.2  404.82
  288.11  405.06  343.34   405.8  395.53  406.88  426.39  408.28  474.18  409.02
#Mann= 4 ,-1 , 0
 -438.38      .1       0  -12.83    .035       0   13.75      .1       0
   233.2     .03       0
#XS Ineff= 4 ,-1
    -450    -150     409    -150 -29.975  407.29  50.295     150  407.29
     150     450     409
Permanent Ineff=
       F       F       F       F
Bank Sta=-12.83,13.75
XS Rating Curve= 0 ,0
Exp/Cntr=0.5,0.3

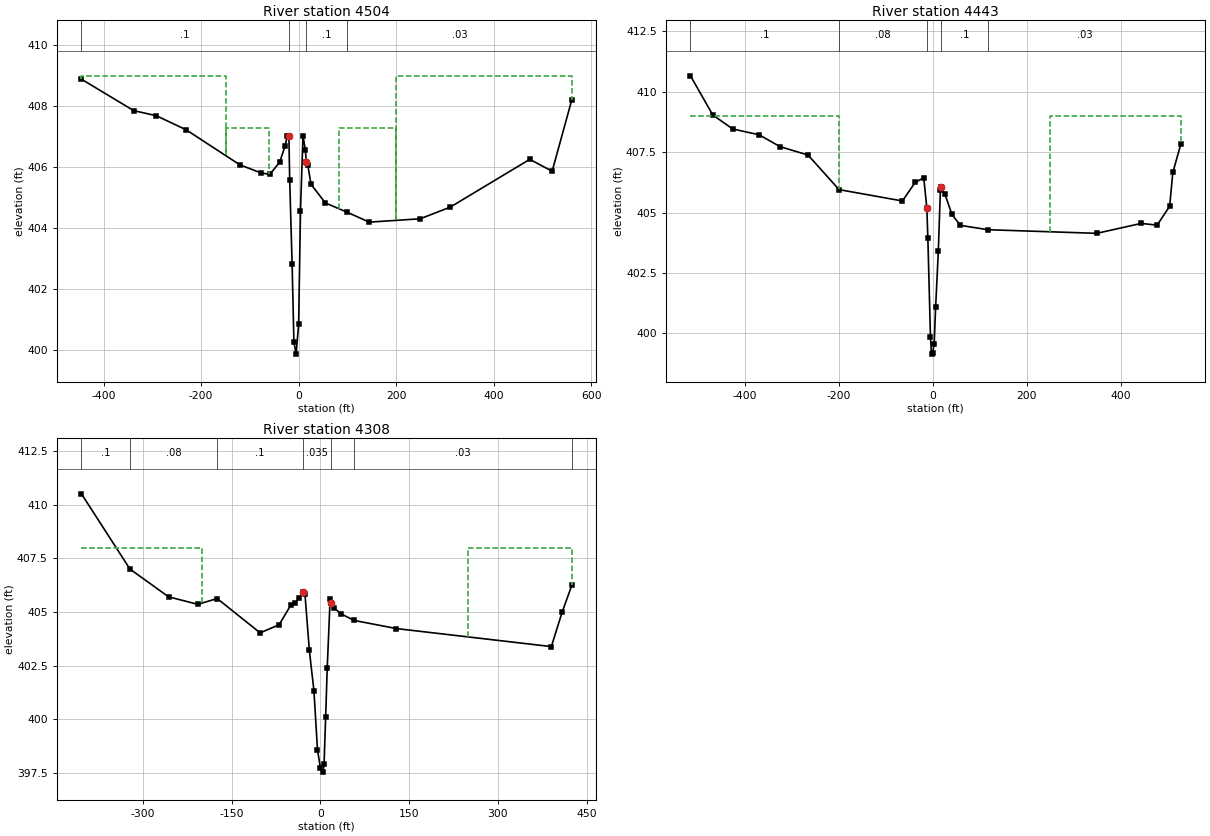
Type RM Length L Ch R = 1 ,4504    ,60.45,61.22,63.53
BEGIN DESCRIPTION:
4504 - BR CS #1
END DESCRIPTION:
#Sta/Elev= 30
 -445.47  408.89 -338.46  407.86 -291.73  407.69 -230.77  407.23 -120.57  406.08
  -76.42  405.81  -58.99  405.77  -38.83  406.17  -27.85   406.7  -23.28  407.04
  -20.05  407.04  -18.36  405.58  -13.39  402.82   -9.73  400.27   -5.18  399.87
       0  400.86    3.76  404.57    8.92  407.04   13.73  406.57   15.78  406.17
   18.56  406.09   25.43  405.44   54.84  404.83  100.18  404.52  144.88   404.2
  249.14  404.31  310.63  404.69  473.99  406.26  519.91  405.87  560.32  408.22
#Mann= 4 ,-1 , 0
 -445.47      .1       0  -20.05    .035       0   15.78      .1       0
  100.18     .03       0
#XS Ineff= 4 ,-1
    -450    -150     409    -150 -61.475  407.29  81.795     200  407.29
     200     600     409
Permanent Ineff=
       F       F       F       F
Bank Sta=-20.05,15.78
XS Rating Curve= 0 ,0
Exp/Cntr=0.3,0.1

Type RM Length L Ch R = 1 ,4443    ,131.82,135.3,138.3
BEGIN DESCRIPTION:
4443
END DESCRIPTION:
#Sta/Elev= 30
 -515.27  410.66 -467.85  409.04 -425.47  408.46 -369.24  408.22 -324.94  407.73
 -265.17  407.38 -199.28  405.95   -64.5  405.48  -37.28  406.25   -19.1  406.44
  -12.49  405.18  -10.36  403.94    -4.8  399.85   -2.61  399.14       0  399.19
    3.07  399.56    6.23  401.11    11.9   403.4   16.27  405.93   18.13  406.04
   26.01  405.76   40.85  404.92   58.92  404.47   117.3  404.29  349.01  404.14
  443.32  404.55  477.22  404.48  503.91  405.26  510.65  406.66  527.84  407.84
#Mann= 5 ,-1 , 0
 -515.27      .1       0 -199.28     .08       0  -12.49    .035       0
   18.13      .1       0   117.3     .03       0
#XS Ineff= 2 ,-1
    -525    -200     409     250     530     409
Permanent Ineff=
       F       F
Bank Sta=-12.49,18.13
XS Rating Curve= 0 ,0
Exp/Cntr=0.3,0.1

Type RM Length L Ch R = 1 ,4308    ,0,0,0
BEGIN DESCRIPTION:
4308
END DESCRIPTION:
#Sta/Elev= 29
 -403.68  410.51 -321.62     407 -256.45  405.71 -207.01  405.36 -174.37  405.63
 -101.73  404.03  -69.68  404.41  -50.23  405.31   -43.4  405.41  -35.37  405.67
  -30.16  405.94  -26.03  405.83  -18.61  403.21  -10.85  401.32   -4.91  398.58
       0  397.75    4.44  397.54    6.25  397.94    8.89  400.09   11.56  402.39
   16.44  405.59   18.39  405.42   22.46  405.21   34.54  404.92   56.98  404.61
  128.49  404.23  390.24  403.39  408.46     405  424.86  406.25
#Mann= 7 ,-1 , 0
 -403.68      .1       0 -321.62     .08       0 -174.37      .1       0
  -30.16    .035       0   18.39      .1       0   56.98     .03       0
  424.86      .1       0
#XS Ineff= 2 ,-1
    -410    -200     408     250     425     408
Permanent Ineff=
       F       F
Bank Sta=-30.16,18.39
XS Rating Curve= 0 ,0
Exp/Cntr=0.3,0.1
LCMann Table=0

Chan Stop Cuts=-1
Use User Specified Reach Order=0
Composite Channel Slope=5

--- FayetteCo.g01 (geometry) ---

Geom Title=EXISTING
Program Version=5.06

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
River Reach=Branch of Shaws ,Branch

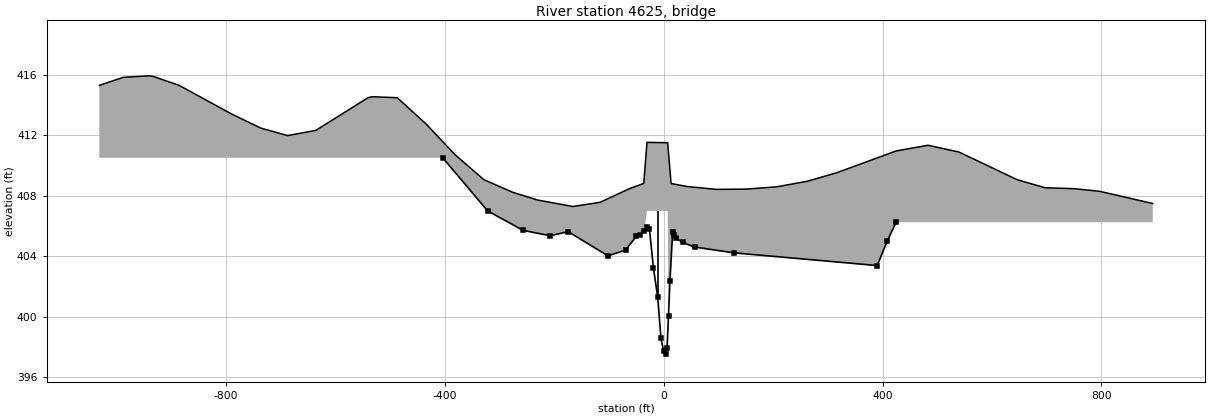
Type RM Length L Ch R = 3 ,4625    ,,,
Bridge Culvert--1,0,-1,-1, 0
Deck Dist Width WeirC Skew NumUp NumDn MinLoCord MaxHiCord MaxSubmerge Is_Ogee
45.85,30.78,2.6,0, 38, 38, , , 0.98, 0, 3,5,,
-1031.15 -987.16 -939.16 -932.12 -885.08 -790.09 -736.09 -687.05 -635.74 -540.02
 -532.39  -486.8 -434.18 -380.57 -328.17 -275.05 -230.43 -165.72 -115.85  -63.17
  -36.31 -30.455   7.375   13.59   42.58   95.82  149.39  206.48  262.04  316.64
  424.94   483.2  539.68  646.14  696.73   750.8   796.8  893.74
 415.293 415.826 415.923 415.878  415.29 413.412 412.469 411.978 412.316 414.481
 414.544 414.477 412.745 410.691 409.055 408.221  407.72  407.29 407.571  408.46
 408.817 411.527 411.504  408.81 408.612 408.424 408.437  408.59 408.954 409.526
 410.961 411.337 410.889  409.06 408.532 408.467 408.294 407.489
     350     350     350     350     350     350     350     350     350     350
     350     350     350     350     350     350     350     350     350     350
     350     407     407     350     350     350     350     350     350     350
     350     350     350     350     350     350     350     350
-1009.45 -965.46 -917.46 -910.42 -863.38 -768.39 -714.39 -665.35 -614.04 -518.32
 -510.69  -465.1 -412.48 -358.87 -306.47 -253.35 -208.73 -144.02  -94.15  -41.47
  -14.61  -8.755  29.075   35.29   64.28  117.52  171.09  228.18  283.74  338.34
  446.64   504.9  561.38  667.84  718.43   772.5   818.5  915.44
 415.293 415.826 415.923 415.878  415.29 413.412 412.469 411.978 412.316 414.481
 414.544 414.477 412.745 410.691 409.055 408.221  407.72  407.29 407.571  408.46
 408.817 411.527 411.504  408.81 408.612 408.424 408.437  408.59 408.954 409.526
 410.961 411.337 410.889  409.06 408.532 408.467 408.294 407.489
     350     350     350     350     350     350     350     350     350     350
     350     350     350     350     350     350     350     350     350     350
     350     407     407     350     350     350     350     350     350     350
     350     350     350     350     350     350     350     350
Pier Skew, UpSta & Num, DnSta & Num=  ,-10.85, 2 ,10.85, 2 , 0 , 0 , 0 ,,
       1       1
     350     407
       1       1
     350     407
BR Coef=-1 , 0 , 0 ,, 0 ,,,0.8,-1,,0,
WSPro=,,,, 1 ,,,, 0 ,,,, 0 ,,,,-1 ,-1 ,-1 , 0 , 0 , 0 , 0 , 0
BC Design=,, 0 ,, 0 ,,,,,,
BC Use User HTab Curves=0
BC User HTab FreeFlow(D)= 0

--- FayetteCo.g02 (geometry) ---

Geom Title=NATURAL
Program Version=5.06

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
River Reach=Branch of Shaws ,Branch

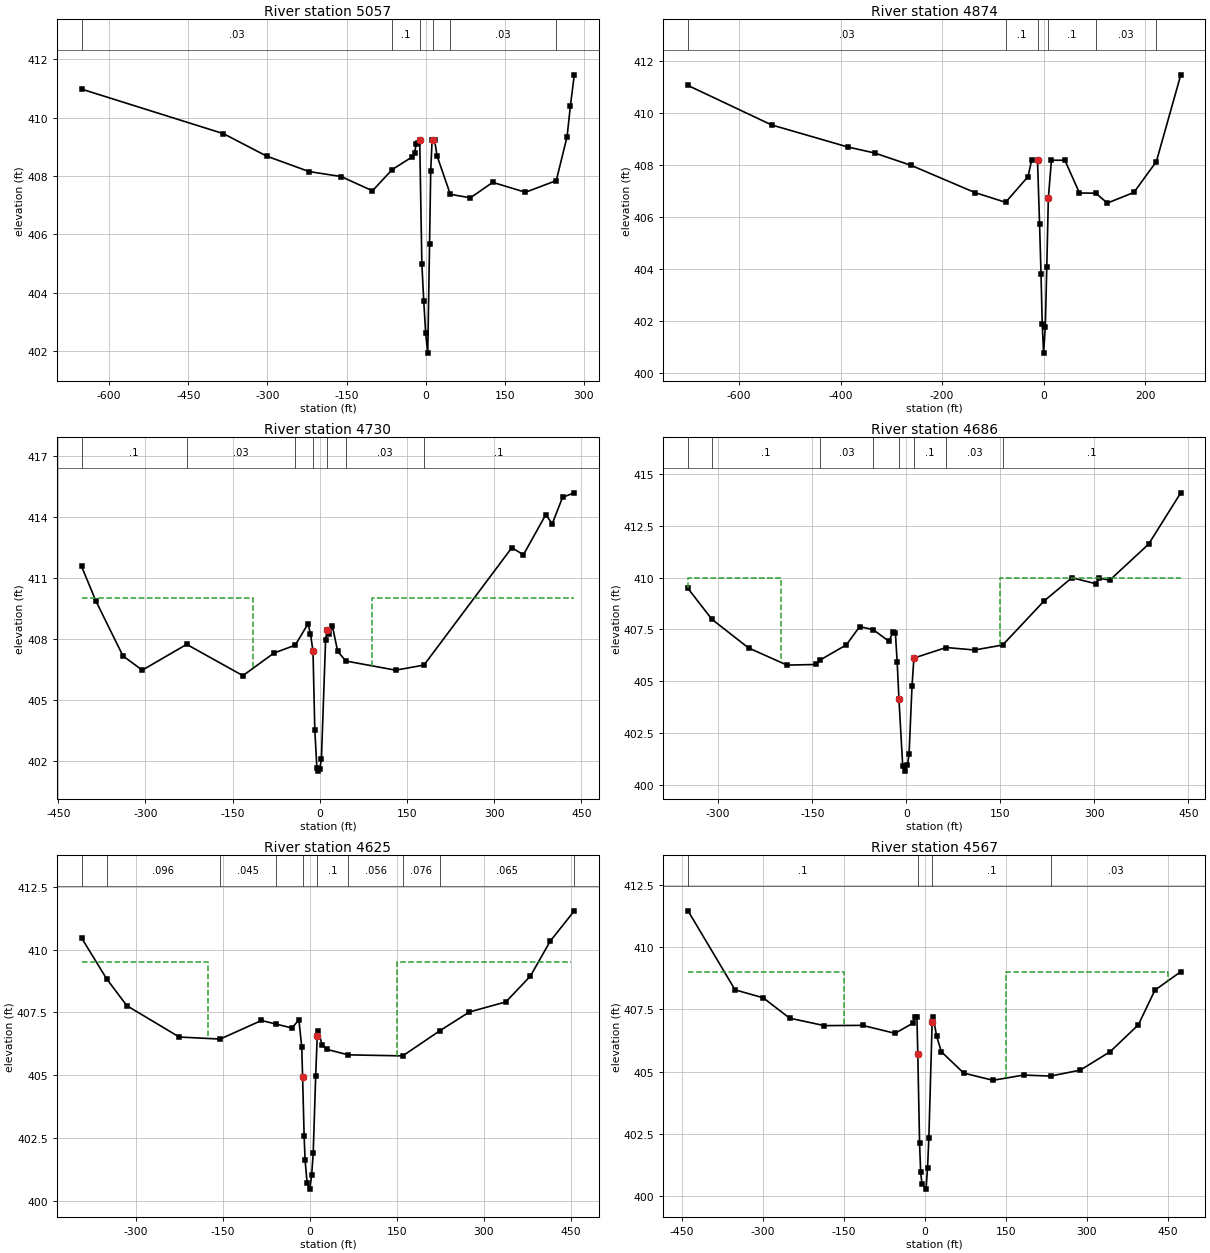
Type RM Length L Ch R = 1 ,5057    ,190.75,182.96,174.42
BEGIN DESCRIPTION:
5057
END DESCRIPTION:
#Sta/Elev= 30
 -652.41  410.98 -383.33  409.45 -301.37  408.68 -220.99  408.15 -160.36  407.98
 -100.86  407.49  -63.38  408.22  -25.79  408.65  -21.04   408.8  -17.95  409.08
  -13.94  409.12  -11.29  409.23   -7.18  404.98   -3.66  403.72       0  402.61
    3.93  401.92    7.41  405.68    9.63  408.18    12.2  409.23   14.26  409.23
   16.97  409.23   21.59  408.69   46.72  407.37   84.82  407.25  127.13  407.78
  189.23  407.44  247.63  407.84  268.17  409.35  274.45  410.41  281.85  411.47
#Mann= 6 ,-1 , 0
 -652.41     .03       0  -63.38      .1       0  -11.29    .035       0
   14.26      .1       0   46.72     .03       0  247.63      .1       0
#XS Ineff= 2 , 0
Permanent Ineff=
       F       F
Bank Sta=-11.29,14.26
XS Rating Curve= 0 ,0
Exp/Cntr=0.3,0.1

Type RM Length L Ch R = 1 ,4874    ,141.25,144.57,149.21
BEGIN DESCRIPTION:
4874
END DESCRIPTION:
#Sta/Elev= 25
 -700.58  411.07 -535.93  409.55 -385.67   408.7 -333.05  408.47 -260.66  407.99
  -134.7  406.94  -74.86  406.57  -30.62  407.56   -23.7  408.19  -11.99  408.19
   -7.96  405.74   -5.07  403.79   -2.76   401.9       0  400.76    3.34  401.77
    6.24  404.06    9.34  406.73   15.42  408.19   41.91  408.19   70.61  406.93
  102.84  406.92   125.6  406.54  177.91  406.95  222.18  408.14  270.27  411.48
#Mann= 6 ,-1 , 0
 -700.58     .03       0  -74.86      .1       0  -11.99    .035       0
    9.34      .1       0  102.84     .03       0  222.18      .1       0
#XS Ineff= 2 , 0
Permanent Ineff=
       F       F
Bank Sta=-11.99,9.34
XS Rating Curve= 0 ,0
Exp/Cntr=0.3,0.1

Type RM Length L Ch R = 1 ,4730    ,38.58,43.64,47.98
BEGIN DESCRIPTION:
4730 - BR CS #4
END DESCRIPTION:
#Sta/Elev= 30
 -409.98  411.57 -385.41  409.87 -338.72  407.16 -305.56  406.46 -229.16  407.73
 -132.38  406.19   -79.1   407.3  -42.39  407.69  -20.42  408.74   -16.1  408.25
  -11.78  407.38    -8.7  403.53   -5.09  401.64   -3.15  401.49       0   401.6
    2.71  402.11    9.91  407.96    12.3  408.42   15.84  408.22   21.67  408.61
   30.67  407.39   44.71  406.91  130.41  406.46  179.15  406.71   330.3  412.49
   350.2  412.14  388.59  414.11  399.86  413.67  417.57  414.97  437.78  415.19
#Mann= 7 ,-1 , 0
 -409.98      .1       0 -229.16     .03       0  -42.39      .1       0
  -11.78    .035       0    12.3      .1       0   44.71     .03       0
  179.15      .1       0
#XS Ineff= 2 ,-1
    -410    -115     410      90     450     410
Permanent Ineff=
       F       F
Bank Sta=-11.78,12.3
XS Rating Curve= 0 ,0
Exp/Cntr=0.3,0.1

Type RM Length L Ch R = 1 ,4686    ,61.94,61.03,60.01
BEGIN DESCRIPTION:
4686 - BR CS #3
END DESCRIPTION:
#Sta/Elev= 30
 -348.15  409.47 -309.97  407.98 -251.64   406.6  -190.2  405.77 -143.96   405.8
 -137.18  406.02  -95.52  406.75  -74.35  407.63  -52.75  407.48  -27.64  406.92
  -20.97  407.39  -17.38  407.33  -14.55  405.93  -11.73  404.14   -5.68   400.9
   -2.02  400.65    1.81  400.94    4.42  401.47    9.16  404.76   12.14  406.11
   63.56  406.62  108.87   406.5  153.75  406.74  219.21  408.85  264.19  409.99
   302.2   409.7  307.65  409.97  324.49  409.87  386.49  411.61  437.85  414.09
#Mann= 8 ,-1 , 0
 -348.15     .03       0 -309.97      .1       0 -137.18     .03       0
  -52.75      .1       0  -11.73    .035       0   12.14      .1       0
   63.56     .03       0  153.75      .1       0
#XS Ineff= 2 ,-1
    -400    -200     410     150     450     410
Permanent Ineff=
       F       F
Bank Sta=-11.73,12.14
XS Rating Curve= 0 ,0
Exp/Cntr=0.3,0.1

Type RM Length L Ch R = 1 ,4625    ,58.94,58.03,57.01
BEGIN DESCRIPTION:
4625
END DESCRIPTION:
#Sta/Elev= 30
 -393.27  410.47 -350.03  408.84 -315.24  407.77 -224.76  406.52 -154.35  406.44
   -83.2  407.18  -58.73  407.04   -30.3  406.88  -18.68  407.21  -13.76  406.12
  -12.28  404.92   -9.62  402.56   -7.97  401.61    -4.5   400.7      .2  400.46
    3.33  401.02       6  401.89   10.26  404.98   12.94  406.55    14.7  406.76
   21.34  406.21   29.28  406.03   66.46  405.81  160.33  405.77  224.12  406.77
  275.27  407.52  338.03  407.92  380.33  408.95  414.49  410.34  456.02  411.55
#Mann= 10 ,-1 , 0
 -393.27    .065       0 -350.03    .096       0 -154.35    .045       0
  -58.73    .071       0  -12.28    .035       0   12.94      .1       0
   66.46    .056       0  160.33    .076       0  224.12    .065       0
  456.02    .065       0
#XS Ineff= 2 ,-1
    -425    -175   409.5     150     450   409.5
Permanent Ineff=
       F       F
Bank Sta=-12.28,12.94
XS Rating Curve= 0 ,0
Exp/Cntr=0.3,0.1

Type RM Length L Ch R = 1 ,4567    ,62.66,62.69,63.44
BEGIN DESCRIPTION:
4567 - BR CS #2
END DESCRIPTION:
#Sta/Elev= 30
 -438.38  411.47 -351.23  408.29 -299.17  407.97 -250.17  407.15 -185.97  406.85
 -115.25  406.86  -54.99  406.54  -21.79  406.95   -17.4   407.2  -14.48   407.2
  -12.83  405.69   -9.58  402.14   -7.56  400.96   -5.23  400.49    2.42  400.27
     5.2  401.12    7.65  402.34   13.75     407   15.57   407.2   21.87  406.44
   30.73   405.8   72.16  404.94  126.33  404.65  182.98  404.86   233.2  404.82
  288.11  405.06  343.34   405.8  395.53  406.88  426.39  408.28  474.18  409.02
#Mann= 4 ,-1 , 0
 -438.38      .1       0  -12.83    .035       0   13.75      .1       0
   233.2     .03       0
#XS Ineff= 2 ,-1
    -450    -150     409     150     450     409
Permanent Ineff=
       F       F
Bank Sta=-12.83,13.75
XS Rating Curve= 0 ,0
Exp/Cntr=0.3,0.1

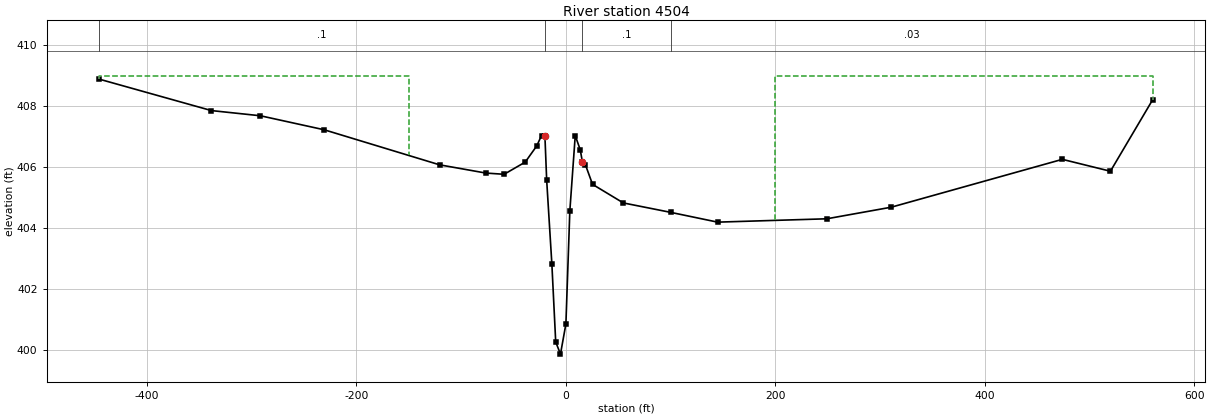
Type RM Length L Ch R = 1 ,4504    ,60.45,61.22,63.53
BEGIN DESCRIPTION:
4504 - BR CS #1
END DESCRIPTION:
#Sta/Elev= 30
 -445.47  408.89 -338.46  407.86 -291.73  407.69 -230.77  407.23 -120.57  406.08
  -76.42  405.81  -58.99  405.77  -38.83  406.17  -27.85   406.7  -23.28  407.04
  -20.05  407.04  -18.36  405.58  -13.39  402.82   -9.73  400.27   -5.18  399.87
       0  400.86    3.76  404.57    8.92  407.04   13.73  406.57   15.78  406.17
   18.56  406.09   25.43  405.44   54.84  404.83  100.18  404.52  144.88   404.2
  249.14  404.31  310.63  404.69  473.99  406.26  519.91  405.87  560.32  408.22
#Mann= 4 ,-1 , 0
 -445.47      .1       0  -20.05    .035       0   15.78      .1       0
  100.18     .03       0
#XS Ineff= 2 ,-1
    -450    -150     409     200     600     409
Permanent Ineff=
       F       F
Bank Sta=-20.05,15.78
XS Rating Curve= 0 ,0
Exp/Cntr=0.3,0.1

--- FayetteCo.g05 (geometry) ---

Geom Title=PROPOSED
Program Version=5.06

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
River Reach=Branch of Shaws ,Branch

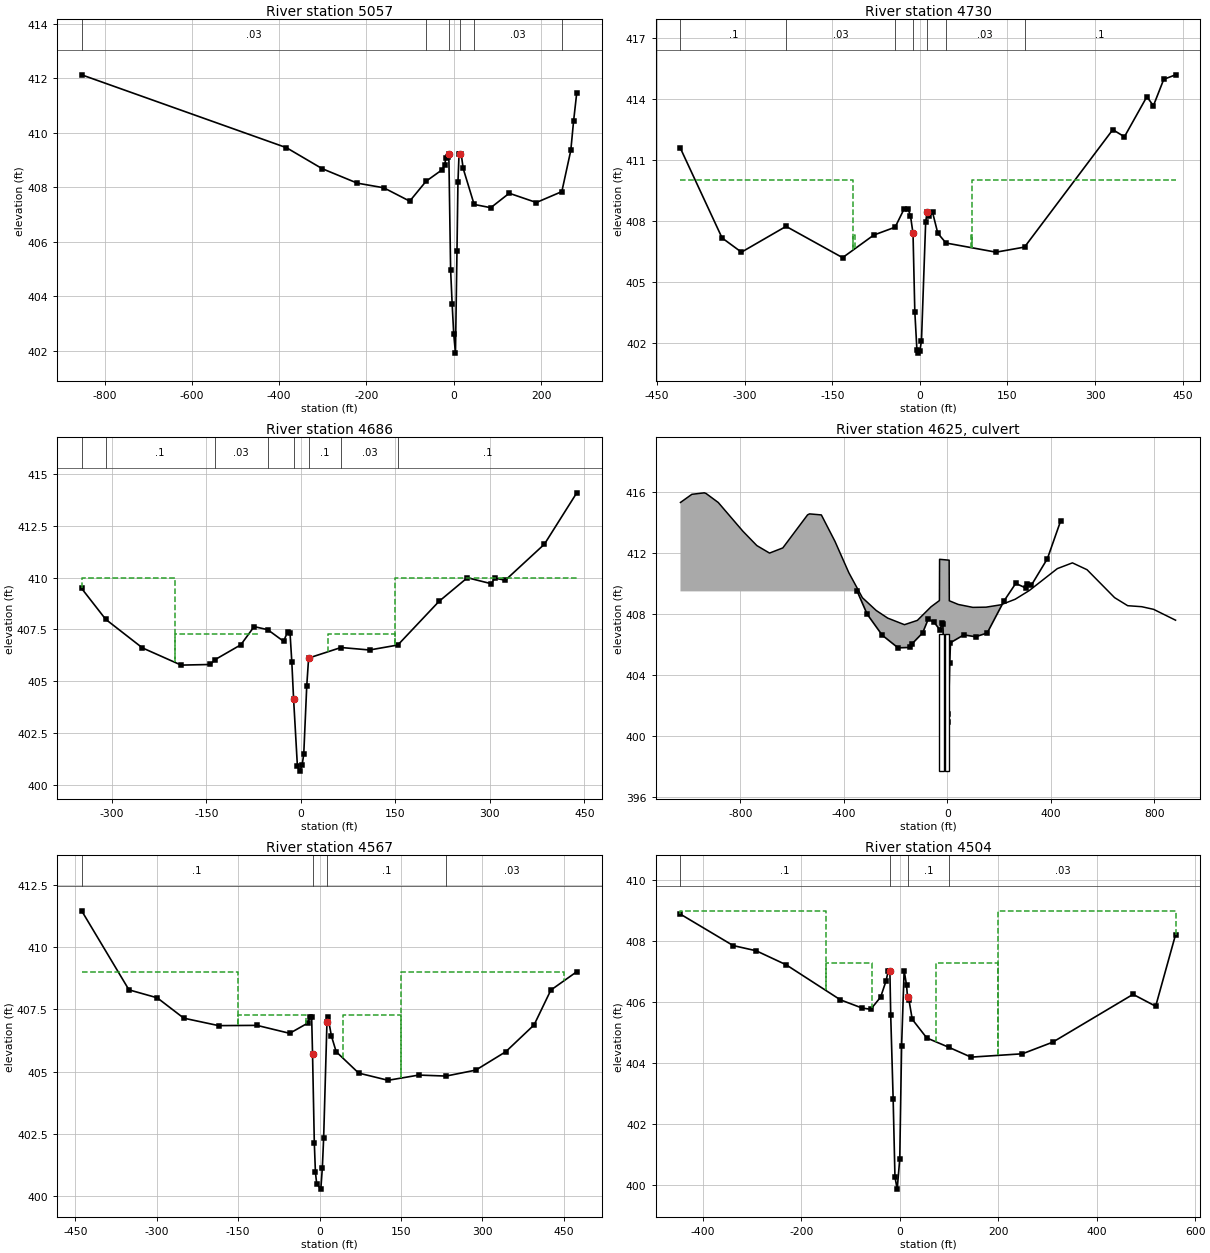
Type RM Length L Ch R = 1 ,5057    ,190.75,182.96,174.42
BEGIN DESCRIPTION:
5057
END DESCRIPTION:
#Sta/Elev= 30
 -852.41  412.12 -383.33  409.45 -301.37  408.68 -220.99  408.15 -160.36  407.98
 -100.86  407.49  -63.38  408.22  -25.79  408.65  -21.04   408.8  -17.95  409.08
  -13.94  409.12  -11.29  409.23   -7.18  404.98   -3.66  403.72       0  402.61
    3.93  401.92    7.41  405.68    9.63  408.18    12.2  409.23   14.26  409.23
   16.97  409.23   21.59  408.69   46.72  407.37   84.82  407.25  127.13  407.78
  189.23  407.44  247.63  407.84  268.17  409.35  274.45  410.41  281.85  411.47
#Mann= 6 ,-1 , 0
 -852.41     .03       0  -63.38      .1       0  -11.29    .035       0
   14.26      .1       0   46.72     .03       0  247.63      .1       0
Bank Sta=-11.29,14.26
XS Rating Curve= 0 ,0
Exp/Cntr=0.3,0.1

Type RM Length L Ch R = 1 ,4730    ,38.58,43.64,47.98
BEGIN DESCRIPTION:
4730 - BR CS #4
END DESCRIPTION:
#Sta/Elev= 30
 -409.98  411.57 -338.72  407.16 -305.56  406.46 -229.16  407.73 -132.38  406.19
   -79.1   407.3  -42.39  407.69  -26.83   408.6  -20.42   408.6   -16.1  408.25
  -11.78  407.38    -8.7  403.53   -5.09  401.64   -3.15  401.49       0   401.6
    2.71  402.11    9.91  407.96    12.3  408.42   15.84  408.22   21.67  408.42
   30.67  407.39   44.71  406.91  130.41  406.46  179.15  406.71   330.3  412.49
   350.2  412.14  388.59  414.11  399.86  413.67  417.57  414.97  437.78  415.19
#Mann= 7 ,-1 , 0
 -409.98      .1       0 -229.16     .03       0  -42.39      .1       0
  -11.78    .035       0    12.3      .1       0   44.71     .03       0
  179.15      .1       0
#XS Ineff= 4 ,-1
    -410    -115     410    -115 -110.53  407.29   87.45      90  407.29
      90     450     410
Permanent Ineff=
       F       F       F       F
Bank Sta=-11.78,12.3
XS Rating Curve= 0 ,0
Exp/Cntr=0.5,0.3

Type RM Length L Ch R = 1 ,4686    ,120.89,119.06,117.02
BEGIN DESCRIPTION:
4686 - BR CS #3
END DESCRIPTION:
#Sta/Elev= 30
 -348.15  409.47 -309.97  407.98 -251.64   406.6  -190.2  405.77 -143.96   405.8
 -137.18  406.02  -95.52  406.75  -74.35  407.63  -52.75  407.48  -27.64  406.92
  -20.97  407.39  -17.38  407.33  -14.55  405.93  -11.73  404.14   -5.68   400.9
   -2.02  400.65    1.81  400.94    4.42  401.47    9.16  404.76   12.14  406.11
   63.56  406.62  108.87   406.5  153.75  406.74  219.21  408.85  264.19  409.99
   302.2   409.7  307.65  409.97  324.49  409.87  386.49  411.61  437.85  414.09
#Mann= 8 ,-1 , 0
 -348.15     .03       0 -309.97      .1       0 -137.18     .03       0
  -52.75      .1       0  -11.73    .035       0   12.14      .1       0
   63.56     .03       0  153.75      .1       0
#XS Ineff= 4 ,-1
    -400    -200     410    -200  -66.53  407.29   43.45     150  407.29
     150     450     410
Permanent Ineff=
       F       F       F       F
Bank Sta=-11.73,12.14
XS Rating Curve= 0 ,0
Exp/Cntr=0.5,0.3

Type RM Length L Ch R = 2 ,4625    ,,,
Bridge Culvert--1,0,-1,-1, 0
Deck Dist Width WeirC Skew NumUp NumDn MinLoCord MaxHiCord MaxSubmerge Is_Ogee
35.99,50.5,2.6,0, 38, 38, 407.29, , 0.98, 0, 3,3,,
-1031.15 -987.16 -939.16 -932.12 -885.08 -790.09 -736.09 -687.05 -635.74 -540.02
 -532.39  -486.8 -434.18 -380.57 -328.17 -275.05 -230.43 -165.72 -115.85  -63.17
 -30.625  -30.04    6.96   7.545   42.58    98.4  149.39  206.48  262.04  316.64
  424.94   483.2  539.68  646.14  696.73   750.8   796.8  881.74
 415.293 415.826 415.923 415.878  415.29 413.412 412.469 411.978 412.316 414.481
 414.544 414.477 412.745 410.691 409.055 408.221  407.72  407.29 407.571  408.46
 408.871  411.57 411.513 408.855 408.612 408.423 408.437  408.59 408.954 409.526
 410.961 411.337 410.889  409.06 408.532 408.467 408.294 407.583
     350     350     350     350     350     350     350     350     350     350
     350     350     350     350     350     350     350     350     350     350
     350     350     350     350     350     350     350     350     350     350
     350     350     350     350     350     350     350     350
-1009.45 -965.46 -917.46 -910.42 -863.38 -768.39 -714.39 -665.35 -614.04 -518.32
 -510.69  -465.1 -412.48 -358.87 -306.47 -253.35 -208.73 -144.02  -94.15  -41.47
      -7   -6.96   28.66  29.245   64.28   120.1  171.09  228.18  283.74  338.34
  446.64   504.9  561.38  667.84  718.43   772.5   818.5  903.44
 415.293 415.826 415.923 415.878  415.29 413.412 412.469 411.978 412.316 414.481
 414.544 414.477 412.745 410.691 409.055 408.221  407.72  407.29 407.571  408.46
 408.871 411.569 411.513 408.855 408.612 408.423 408.437  408.59 408.954 409.526
 410.961 411.337 410.889  409.06 408.532 408.467 408.294 407.583
     350     350     350     350     350     350     350     350     350     350
     350     350     350     350     350     350     350     350     350     350
     350     350     350     350     350     350     350     350     350     350
     350     350     350     350     350     350     350     350
BR Coef=-1 , 0 , 0 ,, 0 ,,,0.8,-1,,0,
WSPro=,,,, 1 ,,,, 0 ,,,, 0 ,,,,-1 ,-1 ,-1 , 0 , 0 , 0 , 0 , 0
Multiple Barrel Culv=2,9,18,54,0.012,0.5,1,10,1,397.7,397.7, 2,Culvert #1  , 0 ,34.235
  -21.54     .16   -1.54   20.16
BC Culvert Barrel=1,18x9 - barrel #1,0
BC Culvert Barrel=2,18x9 - barrel #2,0
Culvert Bottom n=0.035
Culvert Bottom Depth=1.8
Culvert Depth Blocked=1.8
BC Design=,, 0 ,, 0 ,,,,,,
BC Use User HTab Curves=0
BC User HTab FreeFlow(D)= 0

Type RM Length L Ch R = 1 ,4567    ,62.66,62.69,63.44
BEGIN DESCRIPTION:
4567 - BR CS #2
END DESCRIPTION:
#Sta/Elev= 30
 -438.38  411.47 -351.23  408.29 -299.17  407.97 -250.17  407.15 -185.97  406.85
 -115.25  406.86  -54.99  406.54  -21.79  406.95   -17.4   407.2  -14.48   407.2
  -12.83  405.69   -9.58  402.14   -7.56  400.96   -5.23  400.49    2.42  400.27
     5.2  401.12    7.65  402.34   13.75     407   15.57   407.2   21.87  406.44
   30.73   405.8   72.16  404.94  126.33  404.65  182.98  404.86   233.2  404.82
  288.11  405.06  343.34   405.8  395.53  406.88  426.39  408.28  474.18  409.02
#Mann= 4 ,-1 , 0
 -438.38      .1       0  -12.83    .035       0   13.75      .1       0
   233.2     .03       0
#XS Ineff= 4 ,-1
    -450    -150     409    -150  -25.09  407.29   42.42     150  407.29
     150     450     409
Permanent Ineff=
       F       F       F       F
Bank Sta=-12.83,13.75
XS Rating Curve= 0 ,0
Exp/Cntr=0.5,0.3

Type RM Length L Ch R = 1 ,4504    ,60.45,61.22,63.53
BEGIN DESCRIPTION:
4504 - BR CS #1
END DESCRIPTION:
#Sta/Elev= 30
 -445.47  408.89 -338.46  407.86 -291.73  407.69 -230.77  407.23 -120.57  406.08
  -76.42  405.81  -58.99  405.77  -38.83  406.17  -27.85   406.7  -23.28  407.04
  -20.05  407.04  -18.36  405.58  -13.39  402.82   -9.73  400.27   -5.18  399.87
       0  400.86    3.76  404.57    8.92  407.04   13.73  406.57   15.78  406.17
   18.56  406.09   25.43  405.44   54.84  404.83  100.18  404.52  144.88   404.2
  249.14  404.31  310.63  404.69  473.99  406.26  519.91  405.87  560.32  408.22
#Mann= 4 ,-1 , 0
 -445.47      .1       0  -20.05    .035       0   15.78      .1       0
  100.18     .03       0
#XS Ineff= 4 ,-1
    -450    -150     409    -150   -56.6  407.29   73.92     200  407.29
     200     600     409
Permanent Ineff=
       F       F       F       F
Bank Sta=-20.05,15.78
XS Rating Curve= 0 ,0
Exp/Cntr=0.3,0.1

--- FayetteCo.g07 (geometry) ---

Geom Title=PROPOSED - mod 1-21-2020
Program Version=5.07

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
River Reach=Branch of Shaws ,Branch