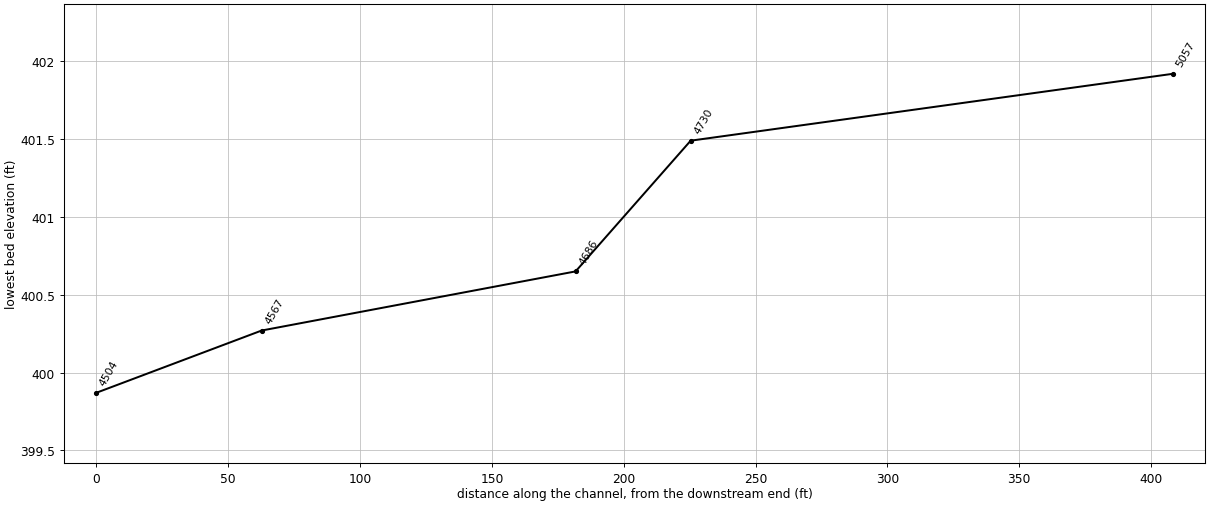
HEC-RAS study FayetteCo.prj: Fayette Co

--- FayetteCo.g07 (geometry) --- (continued)

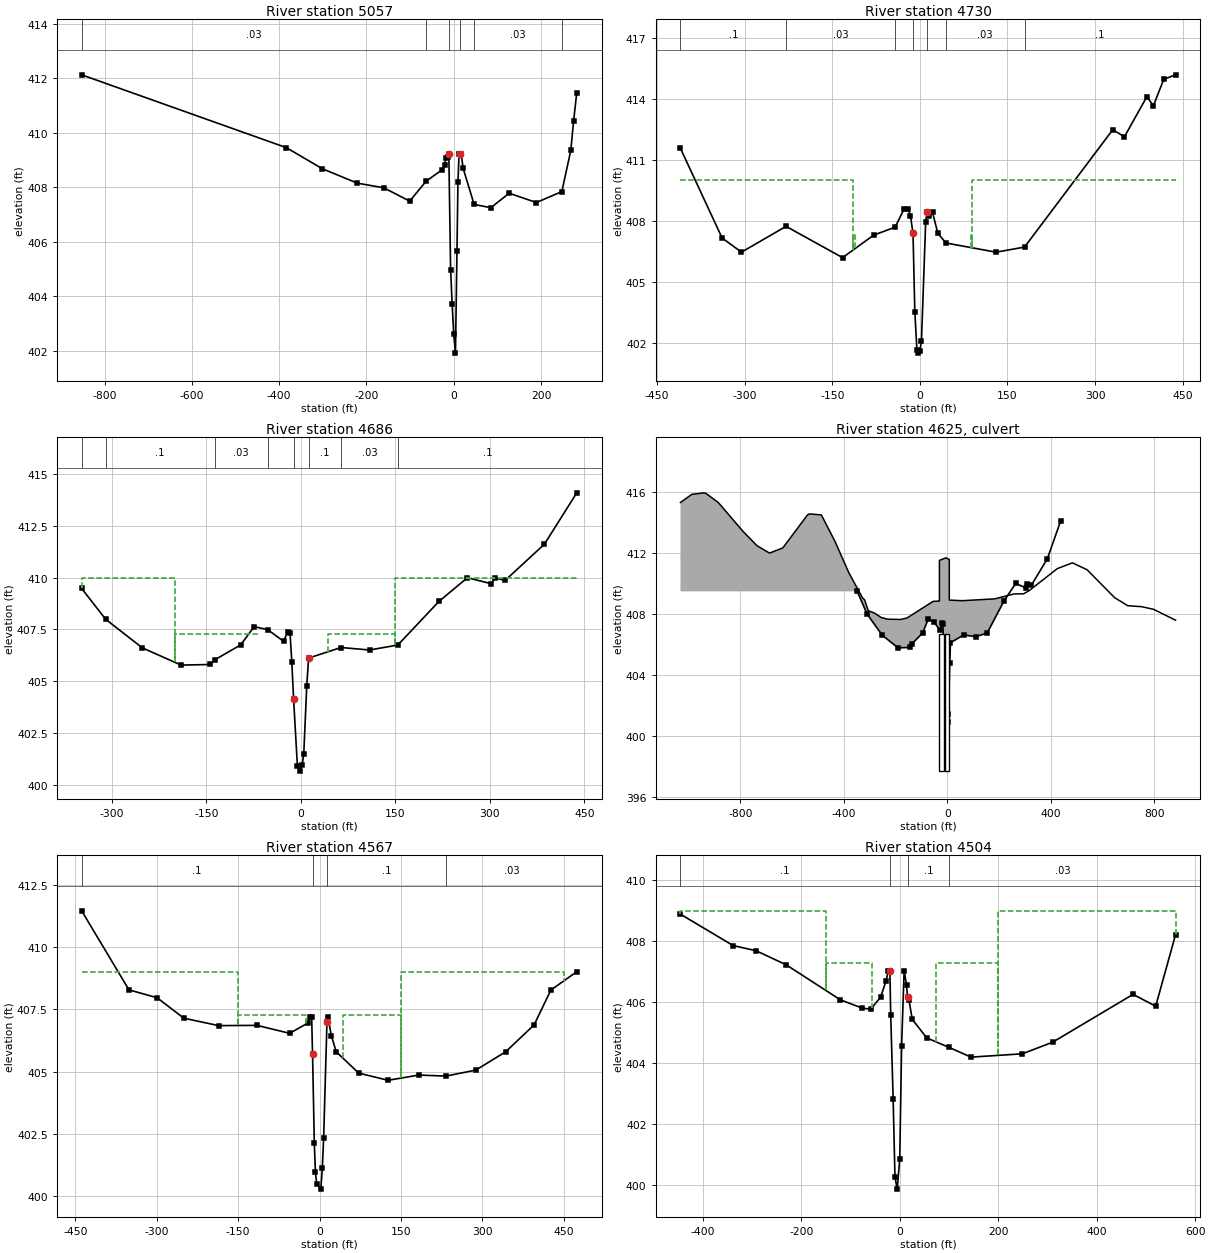
Type RM Length L Ch R = 1 ,5057    ,190.75,182.96,174.42
BEGIN DESCRIPTION:
5057
END DESCRIPTION:
#Sta/Elev= 30
 -852.41  412.12 -383.33  409.45 -301.37  408.68 -220.99  408.15 -160.36  407.98
 -100.86  407.49  -63.38  408.22  -25.79  408.65  -21.04   408.8  -17.95  409.08
  -13.94  409.12  -11.29  409.23   -7.18  404.98   -3.66  403.72       0  402.61
    3.93  401.92    7.41  405.68    9.63  408.18    12.2  409.23   14.26  409.23
   16.97  409.23   21.59  408.69   46.72  407.37   84.82  407.25  127.13  407.78
  189.23  407.44  247.63  407.84  268.17  409.35  274.45  410.41  281.85  411.47
#Mann= 6 ,-1 , 0
 -852.41     .03       0  -63.38      .1       0  -11.29    .035       0
   14.26      .1       0   46.72     .03       0  247.63      .1       0
Bank Sta=-11.29,14.26
XS Rating Curve= 0 ,0
Exp/Cntr=0.3,0.1

Type RM Length L Ch R = 1 ,4730    ,38.58,43.64,47.98
BEGIN DESCRIPTION:
4730 - BR CS #4
END DESCRIPTION:
#Sta/Elev= 30
 -409.98  411.57 -338.72  407.16 -305.56  406.46 -229.16  407.73 -132.38  406.19
   -79.1   407.3  -42.39  407.69  -26.83   408.6  -20.42   408.6   -16.1  408.25
  -11.78  407.38    -8.7  403.53   -5.09  401.64   -3.15  401.49       0   401.6
    2.71  402.11    9.91  407.96    12.3  408.42   15.84  408.22   21.67  408.42
   30.67  407.39   44.71  406.91  130.41  406.46  179.15  406.71   330.3  412.49
   350.2  412.14  388.59  414.11  399.86  413.67  417.57  414.97  437.78  415.19
#Mann= 7 ,-1 , 0
 -409.98      .1       0 -229.16     .03       0  -42.39      .1       0
  -11.78    .035       0    12.3      .1       0   44.71     .03       0
  179.15      .1       0
#XS Ineff= 4 ,-1
    -410    -115     410    -115 -110.53  407.29   87.45      90  407.29
      90     450     410
Permanent Ineff=
       F       F       F       F
Bank Sta=-11.78,12.3
XS Rating Curve= 0 ,0
Exp/Cntr=0.5,0.3

Type RM Length L Ch R = 1 ,4686    ,120.89,119.06,117.02
BEGIN DESCRIPTION:
4686 - BR CS #3
END DESCRIPTION:
#Sta/Elev= 30
 -348.15  409.47 -309.97  407.98 -251.64   406.6  -190.2  405.77 -143.96   405.8
 -137.18  406.02  -95.52  406.75  -74.35  407.63  -52.75  407.48  -27.64  406.92
  -20.97  407.39  -17.38  407.33  -14.55  405.93  -11.73  404.14   -5.68   400.9
   -2.02  400.65    1.81  400.94    4.42  401.47    9.16  404.76   12.14  406.11
   63.56  406.62  108.87   406.5  153.75  406.74  219.21  408.85  264.19  409.99
   302.2   409.7  307.65  409.97  324.49  409.87  386.49  411.61  437.85  414.09
#Mann= 8 ,-1 , 0
 -348.15     .03       0 -309.97      .1       0 -137.18     .03       0
  -52.75      .1       0  -11.73    .035       0   12.14      .1       0
   63.56     .03       0  153.75      .1       0
#XS Ineff= 4 ,-1
    -400    -200     410    -200  -66.53  407.29   43.45     150  407.29
     150     450     410
Permanent Ineff=
       F       F       F       F
Bank Sta=-11.73,12.14
XS Rating Curve= 0 ,0
Exp/Cntr=0.5,0.3

Type RM Length L Ch R = 2 ,4625    ,,,
Bridge Culvert--1,0,-1,-1, 0
Deck Dist Width WeirC Skew NumUp NumDn MinLoCord MaxHiCord MaxSubmerge Is_Ogee
35.99,50.5,2.6,0, 41, 37, 407.29, , 0.98, 0, 3,3,,
-1031.15 -987.16 -939.16 -932.12 -885.08 -790.09 -736.09 -687.05 -635.74 -540.02
 -532.39  -486.8 -434.18 -380.57 -328.17 -319.91 -305.63 -280.63 -255.63 -230.63
 -180.63 -155.63  -55.63  -30.63  -30.62   -5.63    7.55    7.56   57.55  182.55
  257.55  294.39  316.64  424.94   483.2  539.68  646.14  696.73   750.8   796.8
  881.74
 415.293 415.826 415.923 415.878  415.29 413.412 412.469 411.978 412.316 414.481
 414.544 414.477 412.745 410.691 409.055 408.921  408.21  408.04  407.76  407.65
  407.63  407.73  408.81  408.84 411.498 411.668 411.558   408.9  408.86  408.98
   409.3  409.31 409.526 410.961 411.337 410.889  409.06 408.532 408.467 408.294
 407.583
     350     350     350     350     350     350     350     350     350     350
     350     350     350     350     350     350     350     350     350     350
     350     350     350     350     350     350     350     350     350     350
     350     350     350     350     350     350     350     350     350     350
     350
-1009.45 -965.46 -917.46 -910.42 -863.38 -768.39 -714.39 -665.35 -614.04 -518.32
 -510.69  -465.1 -412.48 -358.87 -281.96 -256.96 -231.96 -206.96 -156.96 -131.96
  -31.96   -6.96   -6.95   18.04   31.22   31.23   81.22  206.22  328.59  446.64
   504.9  561.38  667.84  718.43   772.5   818.5  903.44
 415.293 415.826 415.923 415.878  415.29 413.412 412.469 411.978 412.316 414.481
 414.544 414.477 412.745 410.691  408.21  408.04  407.76  407.65  407.63  407.73
  408.81  408.84 411.498 411.668 411.558   408.9  408.86  408.98 409.434 410.961
 411.337 410.889  409.06 408.532 408.467 408.294 407.583
     350     350     350     350     350     350     350     350     350     350
     350     350     350     350     350     350     350     350     350     350
     350     350     350     350     350     350     350     350     350     350
     350     350     350     350     350     350     350
BR Coef=-1 , 0 , 0 ,, 0 ,,,0.8,-1,,0,
WSPro=,,,, 1 ,,,, 0 ,,,, 0 ,,,,-1 ,-1 ,-1 , 0 , 0 , 0 , 0 , 0
Multiple Barrel Culv=2,9,18,54,0.012,0.5,1,10,1,397.7,397.7, 2,Culvert #1  , 0 ,34.235
  -21.54     .16   -1.54   20.16
BC Culvert Barrel=1,18x9 - barrel #1,0
BC Culvert Barrel=2,18x9 - barrel #2,0
Culvert Bottom n=0.035
Culvert Bottom Depth=1.8
Culvert Depth Blocked=1.8
BC Design=,, 0 ,, 0 ,,,,,,
BC Use User HTab Curves=0
BC User HTab FreeFlow(D)= 0

Type RM Length L Ch R = 1 ,4567    ,62.66,62.69,63.44
BEGIN DESCRIPTION:
4567 - BR CS #2
END DESCRIPTION:
#Sta/Elev= 30
 -438.38  411.47 -351.23  408.29 -299.17  407.97 -250.17  407.15 -185.97  406.85
 -115.25  406.86  -54.99  406.54  -21.79  406.95   -17.4   407.2  -14.48   407.2
  -12.83  405.69   -9.58  402.14   -7.56  400.96   -5.23  400.49    2.42  400.27
     5.2  401.12    7.65  402.34   13.75     407   15.57   407.2   21.87  406.44
   30.73   405.8   72.16  404.94  126.33  404.65  182.98  404.86   233.2  404.82
  288.11  405.06  343.34   405.8  395.53  406.88  426.39  408.28  474.18  409.02
#Mann= 4 ,-1 , 0
 -438.38      .1       0  -12.83    .035       0   13.75      .1       0
   233.2     .03       0
#XS Ineff= 4 ,-1
    -450    -150     409    -150  -25.09  407.29   42.42     150  407.29
     150     450     409
Permanent Ineff=
       F       F       F       F
Bank Sta=-12.83,13.75
XS Rating Curve= 0 ,0
Exp/Cntr=0.5,0.3

Type RM Length L Ch R = 1 ,4504    ,60.45,61.22,63.53
BEGIN DESCRIPTION:
4504 - BR CS #1
END DESCRIPTION:
#Sta/Elev= 30
 -445.47  408.89 -338.46  407.86 -291.73  407.69 -230.77  407.23 -120.57  406.08
  -76.42  405.81  -58.99  405.77  -38.83  406.17  -27.85   406.7  -23.28  407.04
  -20.05  407.04  -18.36  405.58  -13.39  402.82   -9.73  400.27   -5.18  399.87
       0  400.86    3.76  404.57    8.92  407.04   13.73  406.57   15.78  406.17
   18.56  406.09   25.43  405.44   54.84  404.83  100.18  404.52  144.88   404.2
  249.14  404.31  310.63  404.69  473.99  406.26  519.91  405.87  560.32  408.22
#Mann= 4 ,-1 , 0
 -445.47      .1       0  -20.05    .035       0   15.78      .1       0
  100.18     .03       0
#XS Ineff= 4 ,-1
    -450    -150     409    -150   -56.6  407.29   73.92     200  407.29
     200     600     409
Permanent Ineff=
       F       F       F       F
Bank Sta=-20.05,15.78
XS Rating Curve= 0 ,0
Exp/Cntr=0.3,0.1